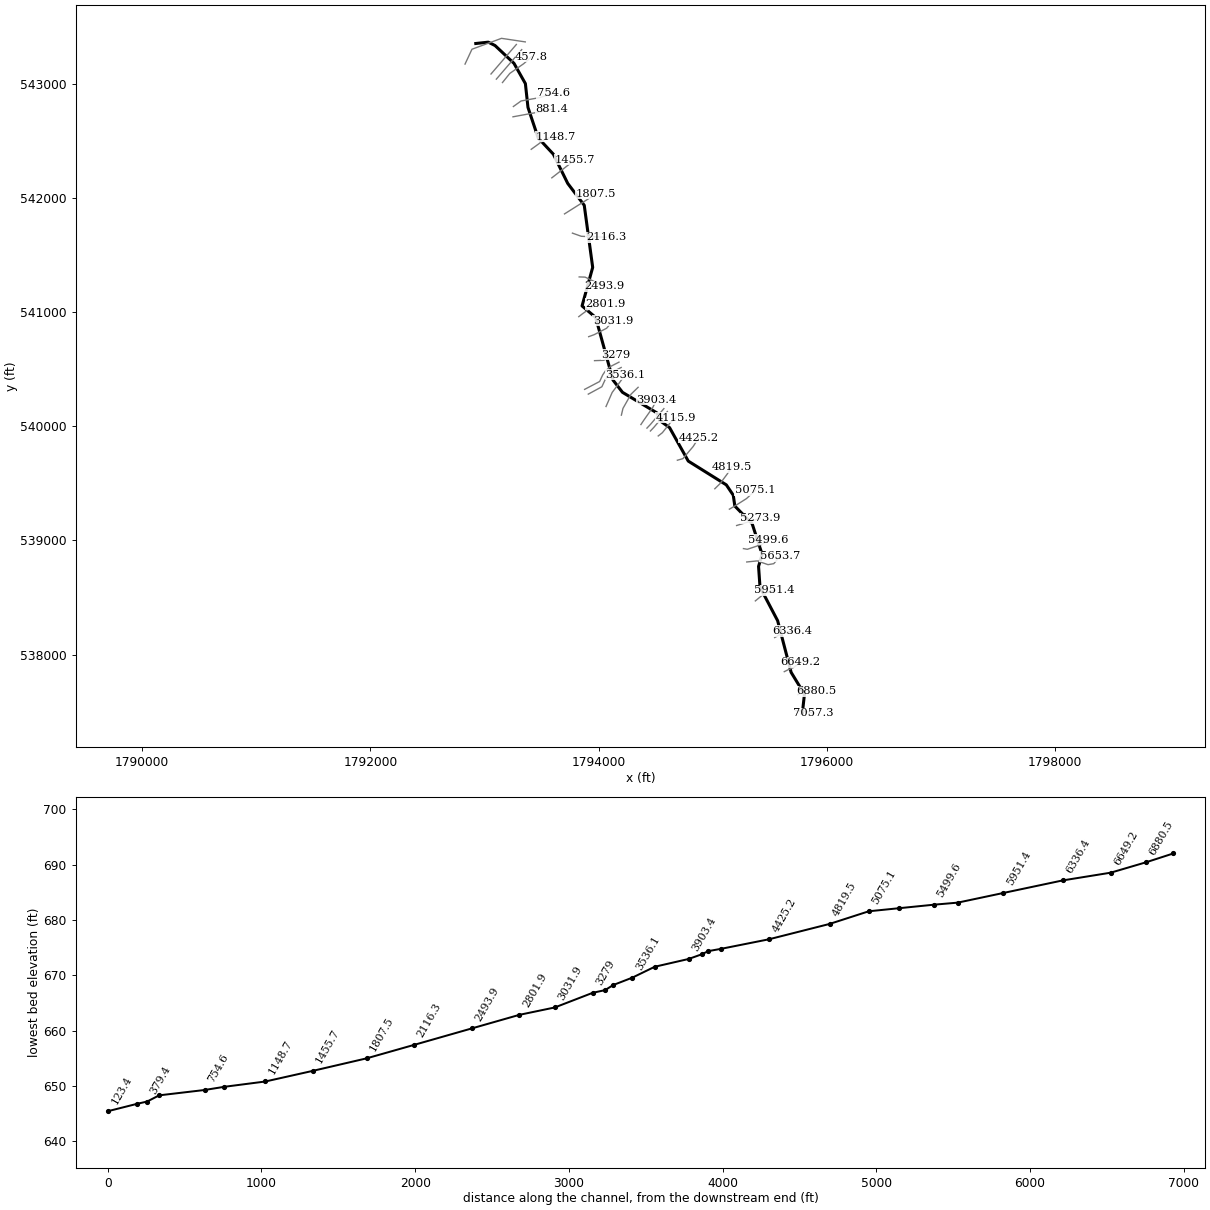
--- SIGMANFK.prj (project) ---

Proj Title=SIGMANFK
Current Plan=p01
Default Exp/Contr=0,0
English Units
Geom File=g01
Flow File=f01
Plan File=p01
BEGIN DESCRIPTION:
END DESCRIPTION:
DSS Export Rating Curves= 0
DSS Export Rating Curve Sorted= 0
DSS Export Volume Flow Curves= 0
DXF OffsetX= 0
DXF OffsetY= 0
DXF ScaleX= 0
DXF ScaleY= 0

--- SIGMANFK.p01 (plan) ---

Plan Title=Floodplain
Program Version=4.00
Geom File=g01
Flow File=f01
K Sum by GR=0
Std Step Tol=0.01
Critical Tol=0.01
Num of Std Step Trials=20
Max Error Tol=0.3
Flow Tol Ratio=0.001
Split Flow NTrial=30
Split Flow Tol=0.02
Split Flow Ratio=0.02
Log Output Level=0
Friction Slope Method=1
Unsteady Friction Slope Method=2
Unsteady Bridges Friction Slope Method=1
Global Log Level=0
CheckData=False
Run HTab=0
Run UNet=0
Run PostProcess=0
UNET Theta=0
UNET Theta Warmup=0
UNET ZTol=0
UNET ZSATol=0
UNET MxIter=0
UNET MaxInSteps=0
UNET DtIC=0
UNET DtMin=0
UNET MaxCRTS=0
UNET WFStab=0
UNET SFStab=0
UNET WFX=0
UNET SFX=0
UNET DSS MLevel=0
UNET DZMax Abort=0
UNET Convert EG Bridges=0
UNET Use Existing IB Tables=0
UNET Froude Limit=0
UNET Froude Power=0
Write IC File=0
Echo Input=False
Echo Output=False
Write Detailed=0

--- SIGMANFK.f01 (steady flow) ---

Flow Title=NFF Regression Equation
Program Version=4.10
Number of Profiles= 1
Profile Names=P100yr
River Rch & RM=SIGMANFK,Main            ,7057.3
886.8607
River Rch & RM=SIGMANFK,Main            ,5075.1
 951.268
River Rch & RM=SIGMANFK,Main            ,4425.2
1005.509
River Rch & RM=SIGMANFK,Main            ,3279
1212.495
River Rch & RM=SIGMANFK,Main            ,457.8
1262.417
Boundary for River Rch & Prof#=SIGMANFK,Main            , 1
Up Type= 0
Dn Type= 3
Dn Slope=0.003
DSS Import GetInterval= 0
DSS Import GetPeak= 0
DSS Import FillOption= 0

--- SIGMANFK.g01 (geometry) ---

Geom Title=USGS 10m DEM
Program Version=4.10

River Reach=SIGMANFK        ,Main
Reach XY= 30
     1795783.852      537485.521     1795802.357       537653.25
     1795685.645      537844.895     1795567.423      538297.326
     1795413.075      538591.422     1795400.287      538772.974
     1795431.872      538878.131     1795344.297      539146.672
     1795192.589      539301.492     1795178.701      539396.978
     1795117.937      539487.256     1794784.603      539695.589
     1794620.723      539988.657     1794550.026      540039.901
     1794508.719      540118.632     1794208.214       540298.02
     1794124.881      540405.658     1793973.204      540953.963
     1793854.048      541054.964     1793947.162      541392.766
     1793873.145      541936.908     1793728.412      542128.443
     1793602.312      542384.825     1793469.492      542527.072
     1793380.089      542794.547      1793357.52      543002.881
      1793257.52      543180.485     1793091.693      543336.342
     1793032.665      543365.856     1792922.943      543354.161

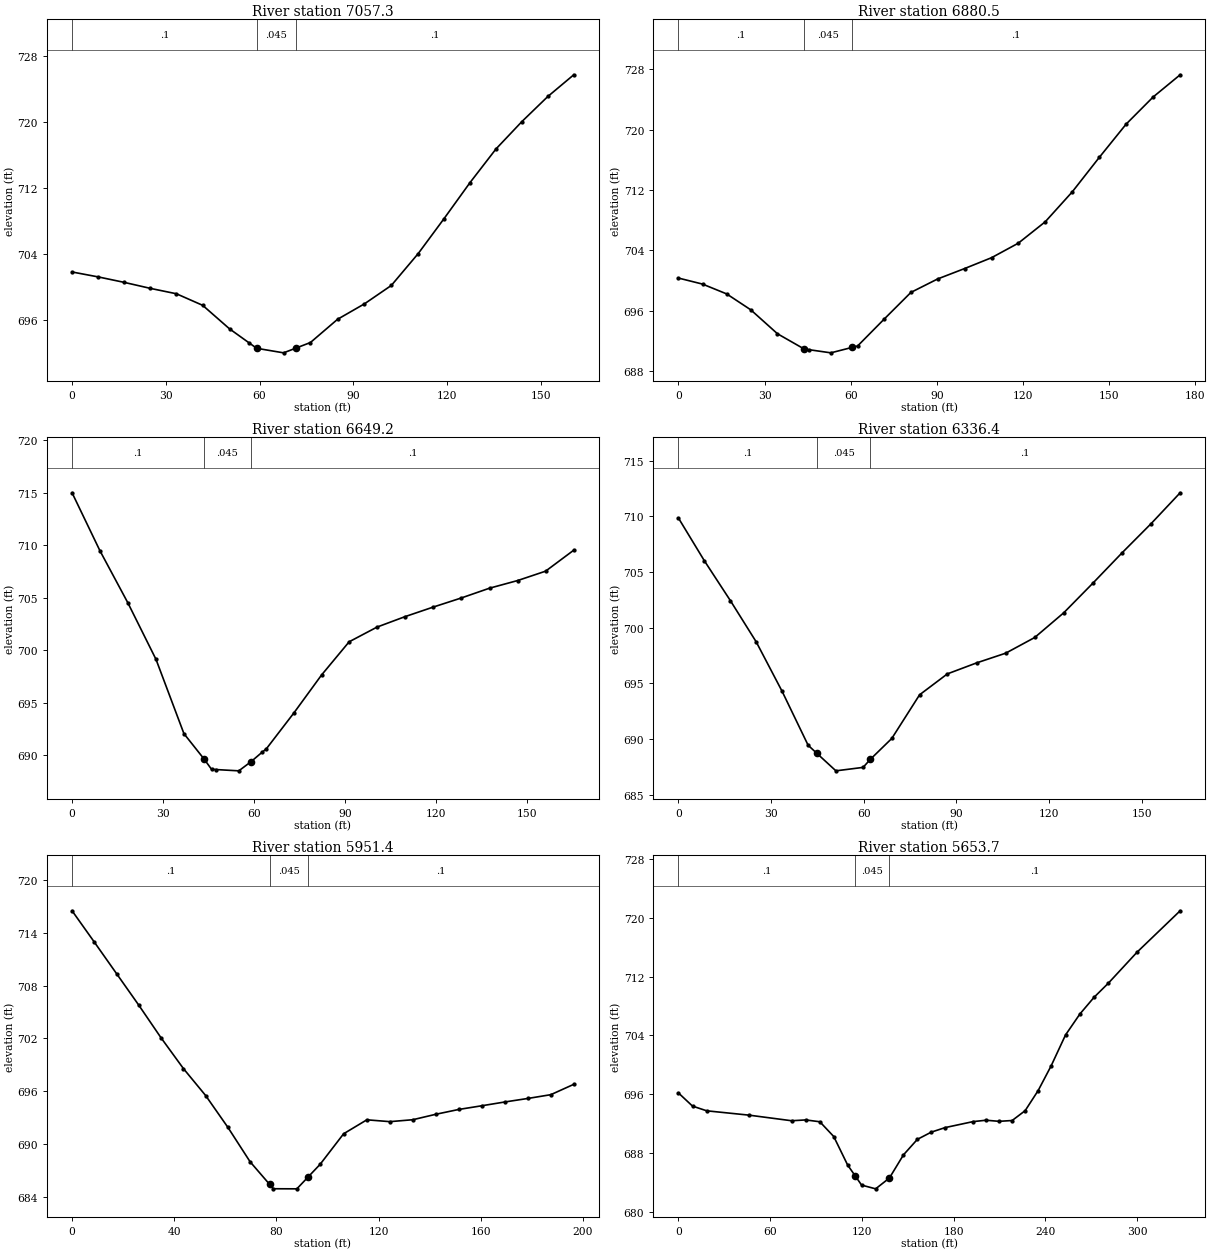
Type RM Length L Ch R = 1 ,7057.3  ,161.8,176.8,191.7
XS GIS Cut Line= 4
     1795722.839      537510.526     1795764.506      537507.054
     1795833.082      537499.241     1795880.825      537485.352
#Sta/Elev= 22
       0  701.82     8.4  701.22    16.7  700.56    25.1  699.83    33.4  699.18
    41.8  697.78    50.4  694.93    56.7  693.22    59.1  692.57    67.7  692.02
    71.7   692.6    76.3  693.27      85  696.09    93.6  697.96   102.2  700.19
   110.8  704.05   119.1   708.3   127.4  712.66   135.7  716.73     144  720.05
   152.3  723.09   160.6  725.72
#Mann= 3 , 0 , 0
       0      .1       0    59.1    .045       0    71.7      .1       0
Bank Sta=59.1,71.7
XS Rating Curve= 0 ,0
Exp/Cntr=0.3,0.1

Type RM Length L Ch R = 1 ,6880.5  ,234.6,231.3,227.8
XS GIS Cut Line= 4
     1795743.672      537648.547     1795766.242      537659.832
     1795821.797      537693.686     1795905.131      537679.797
#Sta/Elev= 22
       0  700.34     8.4  699.54    16.8  698.24    25.2  696.13    34.5  692.96
    43.8  690.94    45.6  690.84    53.1  690.43    60.6  691.16    62.4  691.33
    71.7  694.91      81  698.44    90.3  700.22    99.7   701.6   109.1  703.04
   118.4  704.96   127.8   707.8   137.2  711.76   146.6  716.32     156  720.75
   165.4  724.34   174.8  727.28
#Mann= 3 , 0 , 0
       0      .1       0    43.8    .045       0    60.6      .1       0
Bank Sta=43.8,60.6
XS Rating Curve= 0 ,0
Exp/Cntr=0.3,0.1

Type RM Length L Ch R = 1 ,6649.2  ,311.4,312.8,312.8
XS GIS Cut Line= 4
     1795625.617      537850.804     1795658.603      537867.297
      1795708.95       537888.13      1795767.11      537934.137
#Sta/Elev= 23
       0     715     9.2  709.48    18.4  704.53    27.7  699.14    36.9  692.08
   43.53  689.67      46  688.69    47.6  688.66      55  688.54   58.99   689.4
    62.6  690.29    64.1  690.64    73.2  694.06    82.3  697.66    91.4  700.82
   100.6  702.22   109.9  703.22   119.2  704.13   128.4  704.99   137.7  705.92
     147  706.65   156.2  707.54   165.5  709.54
#Mann= 3 , 0 , 0
       0      .1       0   43.53    .045       0   58.99      .1       0
Bank Sta=43.53,58.99
XS Rating Curve= 0 ,0
Exp/Cntr=0.3,0.1

Type RM Length L Ch R = 1 ,6336.4  ,381.4,385,389.3
XS GIS Cut Line= 4
     1795541.415      538149.415     1795577.874      538170.248
      1795619.54      538187.609     1795692.457      538206.707
#Sta/Elev= 21
       0  709.85     8.4  706.01    16.8  702.44    25.2  698.72    33.6  694.27
      42  689.44    44.8  688.72      51  687.14    59.8  687.45   62.18  688.18
    69.1  690.05    78.1  693.97    87.1  695.85    96.6  696.84     106  697.71
   115.4  699.12   124.8  701.34   134.2  703.99   143.7  706.73   153.1  709.35
   162.5  712.12
#Mann= 3 , 0 , 0
       0      .1       0    44.8    .045       0   62.18      .1       0
Bank Sta=44.8,62.18
XS Rating Curve= 0 ,0
Exp/Cntr=0.3,0.1

Type RM Length L Ch R = 1 ,5951.4  ,319.5,297.7,276.6
XS GIS Cut Line= 4
     1795372.145      538470.595     1795425.964      538514.866
     1795464.158       538540.04     1795541.415      538564.345
#Sta/Elev= 25
       0  716.54     8.7  712.98    17.4  709.39    26.1   705.8    34.8  702.09
    43.6  698.57    52.3   695.5      61  691.88    69.7  687.96    77.3   685.4
    78.8  684.89      88  684.88    92.3   686.2    97.1  687.67   106.3  691.15
   115.4  692.74   124.4  692.53   133.4  692.75   142.4  693.37   151.4  693.92
   160.4  694.34   169.4  694.77   178.4  695.17   187.4   695.6   196.4  696.78
#Mann= 3 , 0 , 0
       0      .1       0    77.3    .045       0    92.3      .1       0
Bank Sta=77.3,92.3
XS Rating Curve= 0 ,0
Exp/Cntr=0.3,0.1

Type RM Length L Ch R = 1 ,5653.7  ,139,154.2,169.3
XS GIS Cut Line= 5
     1795296.624      538811.741     1795388.638       538821.29
     1795483.256      538788.304     1795533.603      538796.984
      1795588.29       538861.22
#Sta/Elev= 30
       0  696.17     9.2  694.38    18.5  693.74    46.2  693.15      74  692.39
    83.3   692.5    92.5  692.25   101.6  690.24   110.7  686.36   115.8  684.84
   119.8  683.64     129  683.13     138   684.6   147.2  687.75   156.3  689.86
   165.4  690.84   174.5  691.46   192.7  692.27   201.2  692.46   209.7  692.31
   218.3  692.42   226.8  693.76   235.3  696.49   243.8  699.85   253.2  704.05
   262.6   706.9   271.9  709.18   281.3  711.11     300  715.31   328.2  720.94
#Mann= 3 , 0 , 0
       0      .1       0   115.8    .045       0     138      .1       0
Bank Sta=115.8,138
XS Rating Curve= 0 ,0
Exp/Cntr=0.3,0.1

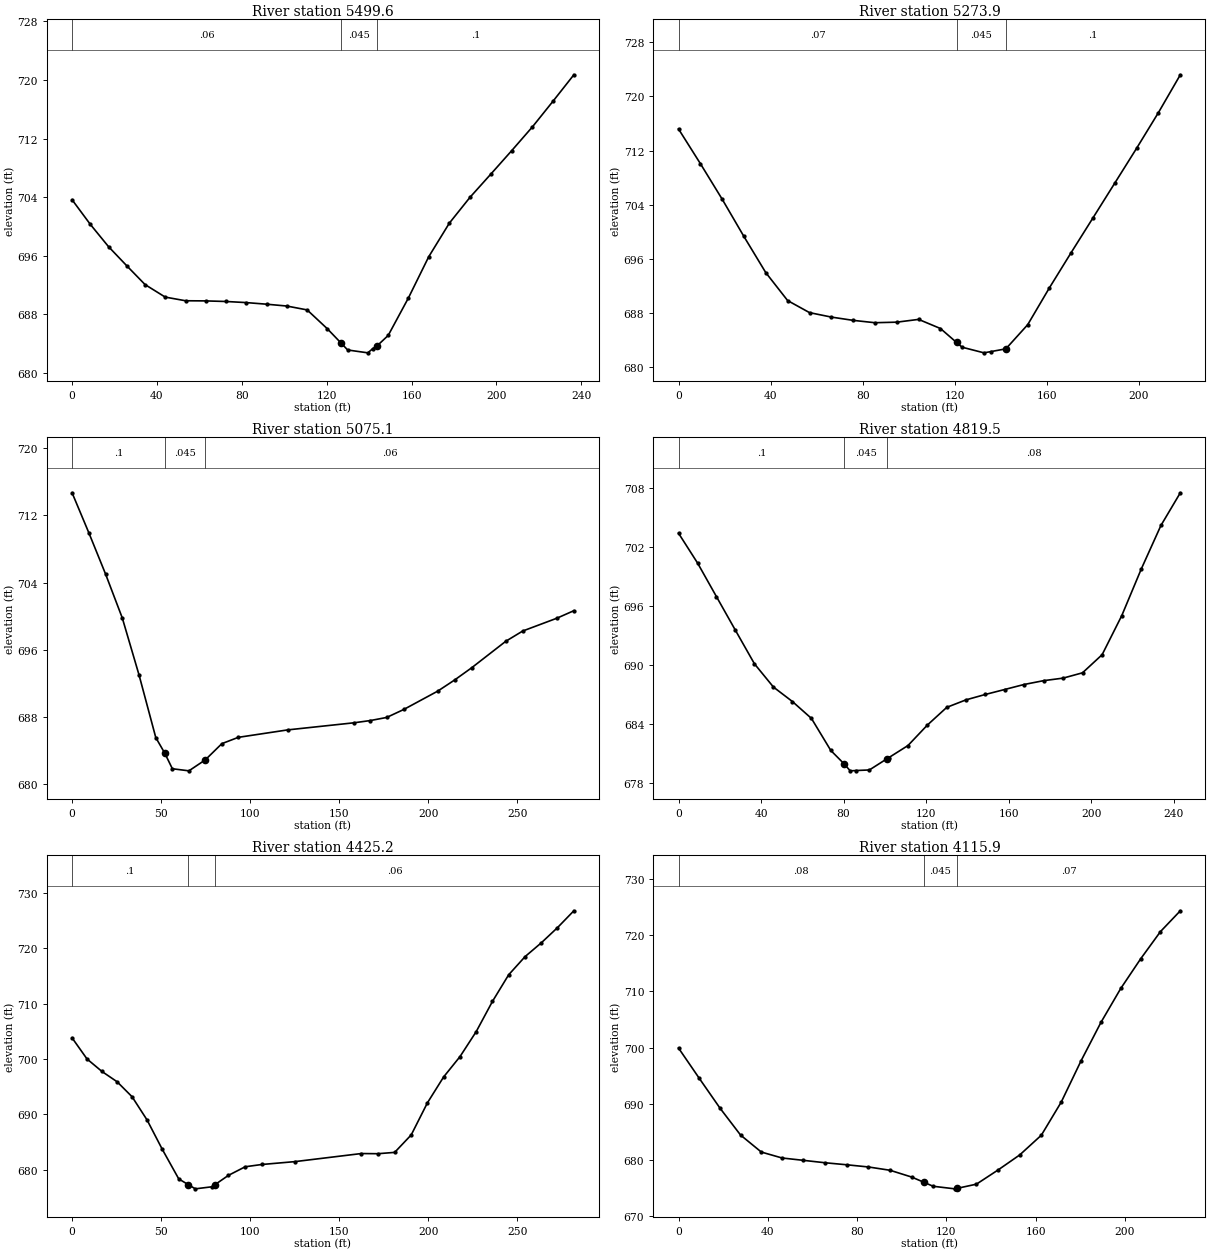
Type RM Length L Ch R = 1 ,5499.6  ,226.3,225.6,225
XS GIS Cut Line= 4
     1795267.978      538928.929     1795301.832      538922.852
     1795428.568      538965.387     1795484.124      539005.318
#Sta/Elev= 29
       0  703.66     8.6   700.3    17.2  697.25    25.8  694.64    34.4  692.08
    43.9  690.37    53.5  689.87      63  689.85    72.6  689.77    82.1  689.62
    91.7   689.4   101.2  689.15   110.8  688.62   120.3  686.05   126.7  684.12
   129.9  683.15   139.4  682.76   141.7  683.33  143.93  683.76     149  685.14
   158.5  690.24   168.1  695.88   177.8  700.46   187.6  704.01   197.4  707.17
   207.2  710.36     217  713.62   226.7  717.12   236.5  720.72
#Mann= 3 , 0 , 0
       0     .06       0   126.7    .045       0  143.93      .1       0
Bank Sta=126.7,143.93
XS Rating Curve= 0 ,0
Exp/Cntr=0.3,0.1

Type RM Length L Ch R = 1 ,5273.9  ,193.7,198.8,204.8
XS GIS Cut Line= 2
     1795208.082      539131.186     1795416.415      539195.422
#Sta/Elev= 26
       0  715.19     9.5  710.07      19   704.8    28.4  699.32    37.9  693.98
    47.4  689.85    56.9  688.07    66.4  687.41    75.8  686.93    85.3  686.58
    94.8  686.66   104.3  687.07   113.8  685.72   120.8  683.66   123.2  682.96
   132.7  682.13   135.8  682.32   142.2  682.72   151.7  686.29   161.1  691.72
   170.6  696.95   180.1  702.09   189.6  707.24     199  712.34   208.5  717.62
     218   723.2
#Mann= 3 , 0 , 0
       0     .07       0   120.8    .045       0   142.2      .1       0
Bank Sta=120.8,142.2
XS Rating Curve= 0 ,0
Exp/Cntr=0.3,0.1

Type RM Length L Ch R = 1 ,5075.1  ,246.6,255.6,263.7
XS GIS Cut Line= 4
     1795144.714      539274.415     1795185.513      539297.852
     1795294.888      539367.297     1795372.145      539438.477
#Sta/Elev= 24
       0   714.7     9.4  709.94    18.8  705.02    28.2  699.78    37.6  692.99
      47  685.53   52.08  683.66    56.3  681.82    65.6  681.57    74.8  682.88
    84.1  684.81    93.3  685.56   121.1  686.45   158.1  687.29   167.4  687.56
   176.6  687.93   186.2  688.88   205.3  691.07   214.8   692.4   224.4  693.86
   243.5  697.01     253  698.23   272.1  699.75   281.7  700.65
#Mann= 3 , 0 , 0
       0      .1       0   52.08    .045       0    74.8     .06       0
Bank Sta=52.08,74.8
XS Rating Curve= 0 ,0
Exp/Cntr=0.3,0.1

Type RM Length L Ch R = 1 ,4819.5  ,396,394.3,392.9
XS GIS Cut Line= 4
      1795017.11      539453.234     1795063.117      539498.373
     1795124.749      539580.838     1795166.415      539644.207
#Sta/Elev= 30
       0  703.42     9.2   700.4    18.4  696.97    27.6  693.55    36.8  690.15
      46  687.79    55.2  686.32    64.4  684.61    73.8  681.35   80.38  679.96
    83.2  679.28    85.9  679.31    92.5  679.37   100.9  680.49   101.9  680.62
   111.2  681.85   120.6  683.93     130  685.73   139.3  686.49   148.7  687.04
     158  687.54   167.4  688.05   176.9  688.44   186.4   688.7   195.8  689.24
   205.3  691.08   214.8  695.04   224.3   699.8   233.8  704.21   243.2  707.53
#Mann= 3 , 0 , 0
       0      .1       0   80.38    .045       0   100.9     .08       0
Bank Sta=80.38,100.9
XS Rating Curve= 0 ,0
Exp/Cntr=0.3,0.1

Type RM Length L Ch R = 1 ,4425.2  ,307.7,309.3,310.4
XS GIS Cut Line= 4
     1794688.985      539703.234     1794737.596      539717.123
     1794827.874      539823.894     1794876.485      539901.151
#Sta/Elev= 30
       0   703.8     8.4  699.98    16.8  697.72    25.3  695.86    33.7  693.15
    42.1  688.96    50.6  683.68    59.9   678.3    65.2  677.28    69.2  676.51
    78.5  676.88    80.2  677.26    87.8  678.95    97.2   680.5   106.5  680.91
   125.1  681.43   162.4  682.89   171.7  682.86   181.1   683.1   190.4  686.26
   199.5  692.06   208.6  696.74   217.8  700.42   226.9  704.94     236  710.39
   245.1   715.2   254.3  718.48   263.4  720.97   272.5  723.72   281.7  726.77
#Mann= 3 , 0 , 0
       0      .1       0    65.2    .045       0    80.2     .06       0
Bank Sta=65.2,80.2
XS Rating Curve= 0 ,0
Exp/Cntr=0.3,0.1

Type RM Length L Ch R = 1 ,4115.9  ,86.2,85.5,84.8
XS GIS Cut Line= 4
      1794521.45      539915.908     1794557.908      539944.554
     1794629.957        540035.7     1794678.568      540074.762
#Sta/Elev= 27
       0   699.9     9.3   694.5    18.6  689.18    27.8  684.39    37.1  681.36
    46.4   680.3      56  679.88    65.7  679.45    75.4  679.09    85.1   678.7
    94.8  678.11   104.5   676.9   109.9  675.98   114.1  675.26   123.8   674.8
   124.9  674.89   133.5  675.63   143.2  678.16   152.9  680.84   162.6  684.36
   171.5  690.25   180.4  697.62   189.3  704.46   198.2  710.53   207.1   715.8
     216  720.67   224.9  724.38
#Mann= 3 , 0 , 0
       0     .08       0   109.9    .045       0   124.9     .07       0
Bank Sta=109.9,124.9
XS Rating Curve= 0 ,0
Exp/Cntr=0.3,0.1

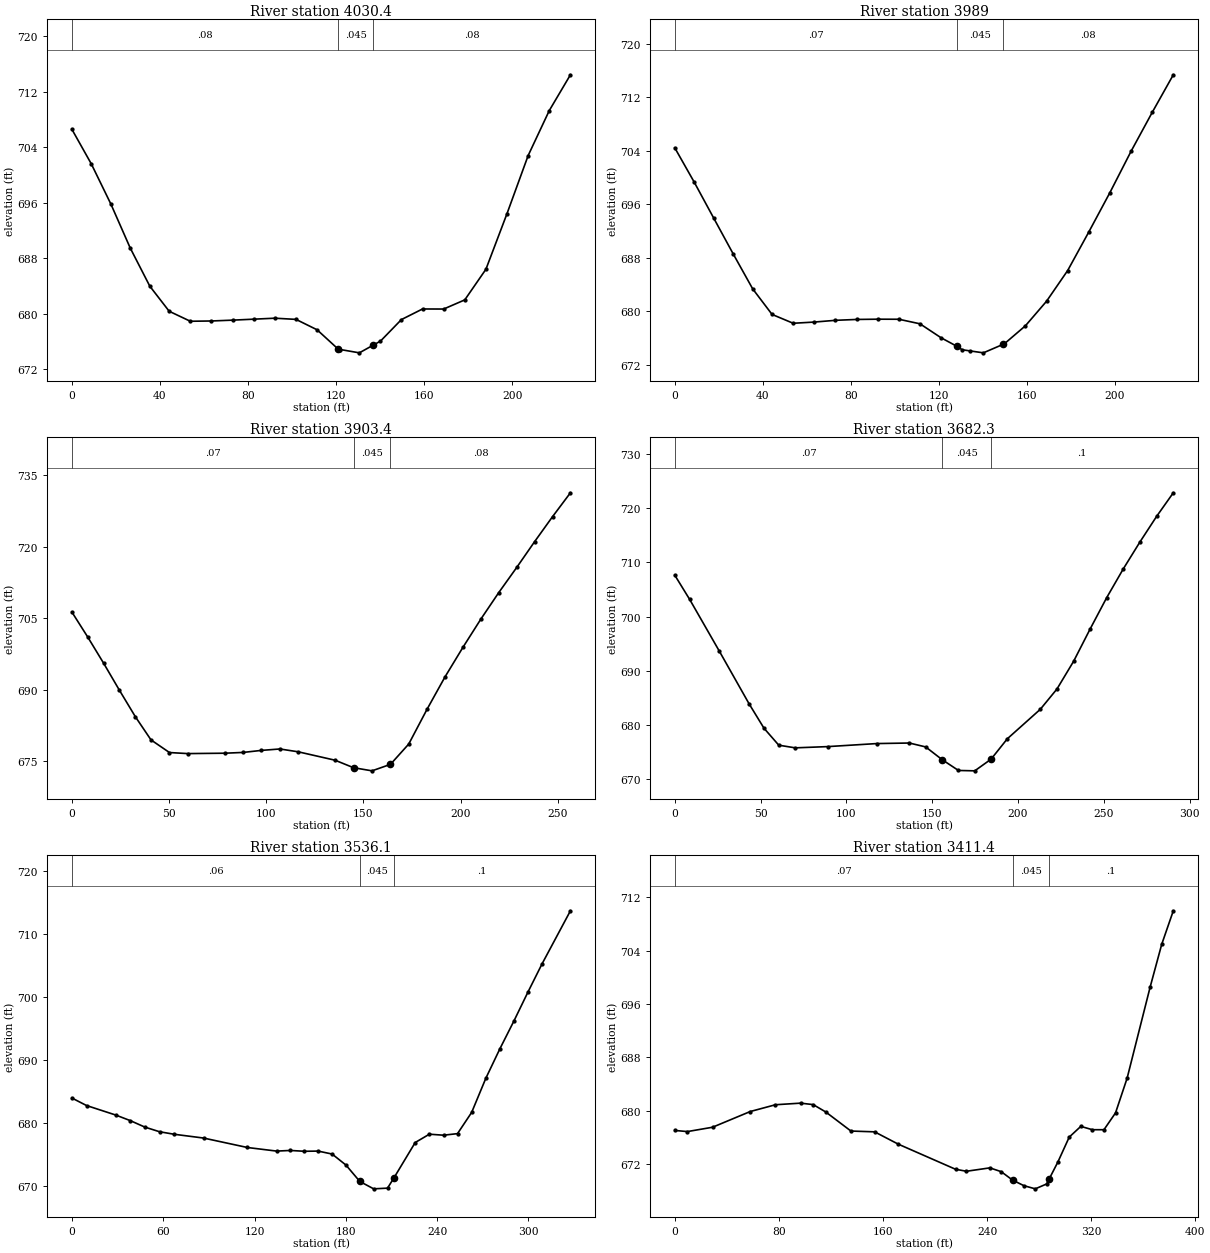
Type RM Length L Ch R = 1 ,4030.4  ,40.8,41.5,45.1
XS GIS Cut Line= 3
     1794452.874      539959.311     1794483.256      539991.429
     1794601.311      540130.318
#Sta/Elev= 27
       0  706.57     8.8   701.6    17.7  695.81    26.5  689.47    35.4  683.97
    44.2  680.36    53.8  678.92    63.4  678.96      73  679.08    82.6  679.22
    92.2  679.36   101.8  679.19   111.4  677.69     121   674.9   121.9  674.85
   130.6  674.37   136.9  675.48   140.2  676.06   149.7  679.16   159.3  680.69
   168.9  680.68   178.5     682   188.1  686.41   197.7  694.44   207.3   702.8
   216.9  709.28   226.5  714.43
#Mann= 3 , 0 , 0
       0     .08       0     121    .045       0   136.9     .08       0
Bank Sta=121,136.9
XS Rating Curve= 0 ,0
Exp/Cntr=0.3,0.1

Type RM Length L Ch R = 1 ,3989    ,84,85.6,84.2
XS GIS Cut Line= 3
     1794422.492      539984.484     1794452.874      540016.602
     1794570.929      540155.491
#Sta/Elev= 28
       0  704.45     8.8  699.34    17.7  693.94    26.5  688.62    35.4  683.37
    44.2  679.55    53.8  678.23    63.4  678.41      73  678.67    82.6   678.8
    92.2  678.84   101.8  678.83   111.4  678.15     121  676.06  128.21  674.78
   130.6  674.27   134.1   674.1   140.2  673.81   149.1  675.07   149.7  675.15
   159.3  677.85   168.9  681.52   178.5  686.11   188.1  691.87   197.7  697.76
   207.3  703.93   216.9  709.74   226.5  715.37
#Mann= 3 , 0 , 0
       0     .07       0  128.21    .045       0   149.1     .08       0
Bank Sta=128.21,149.1
XS Rating Curve= 0 ,0
Exp/Cntr=0.3,0.1

Type RM Length L Ch R = 1 ,3903.4  ,218.8,221,223.2
XS GIS Cut Line= 4
      1794369.54      540015.734      1794392.11      540049.588
     1794473.707      540165.908     1794506.693       540231.88
#Sta/Elev= 27
       0  706.28     8.1  701.07    16.3  695.56    24.4  689.91    32.6  684.35
    40.7  679.45    50.2   676.8    59.6  676.58    78.6  676.66      88  676.82
    97.5  677.25     107  677.55   116.5  676.95   135.4  675.19   144.9  673.62
   154.4  672.96   163.9  674.32   173.3  678.58   182.8  685.94     192   692.7
   201.2  698.89   210.4   704.8   219.6  710.36   228.9  715.67   238.1  721.08
   247.3  726.31   256.5  731.32
#Mann= 3 , 0 , 0
       0     .07       0   144.9    .045       0   163.9     .08       0
Bank Sta=144.9,163.9
XS Rating Curve= 0 ,0
Exp/Cntr=0.3,0.1

Type RM Length L Ch R = 1 ,3682.3  ,149.1,146.2,143.4
XS GIS Cut Line= 4
     1794198.533        540098.2     1794212.422      540157.227
     1794282.735      540281.359     1794345.235      540342.123
#Sta/Elev= 25
       0  707.63     8.7  703.15      26   693.6    43.3  683.91      52   679.4
    60.6  676.28    70.2  675.79    89.2  676.02   117.7  676.58   136.7  676.68
   146.2  675.96   155.8  673.61   165.3  671.62   174.8  671.55   184.3   673.7
   193.8  677.47     213   682.9   222.7  686.64   232.4  691.75     242  697.69
   251.7   703.5   261.4  708.82   271.1  713.78   280.8  718.49   290.5  722.83
#Mann= 3 , 0 , 0
       0     .07       0   155.8    .045       0   184.3      .1       0
Bank Sta=155.8,184.3
XS Rating Curve= 0 ,0
Exp/Cntr=0.3,0.1

Type RM Length L Ch R = 1 ,3536.1  ,129.2,124.7,119.4
XS GIS Cut Line= 4
     1794063.985       540173.72     1794117.804      540296.984
     1794172.492      540369.901     1794232.388      540452.366
#Sta/Elev= 30
       0  683.99     9.6   682.8    28.8  681.29    38.4   680.4      48  679.37
    57.6  678.64    67.2  678.24    86.5  677.64   115.3  676.14   134.5  675.57
   143.6  675.67   152.7  675.54   161.8  675.57     171   675.1   180.1  673.35
   189.2  670.75   198.3  669.58   207.4  669.69   211.7  671.35   225.6  676.93
   234.9  678.25   244.2  678.09   253.4  678.34   262.7  681.71     272  687.12
   281.2  691.78   290.5  696.23   299.8  700.86     309   705.3   327.6   713.7
#Mann= 3 , 0 , 0
       0     .06       0   189.2    .045       0   211.7      .1       0
Bank Sta=189.2,211.7
XS Rating Curve= 0 ,0
Exp/Cntr=0.3,0.1

Type RM Length L Ch R = 1 ,3411.4  ,52.4,52.2,51.2
XS GIS Cut Line= 6
     1793908.603      540282.227      1794027.58      540346.842
     1794054.436      540404.623     1794078.742      540440.213
     1794125.617      540479.276     1794196.797      540515.734
#Sta/Elev= 30
       0  677.01     9.7  676.84      29  677.49      58  679.85    77.4  680.87
    96.7  681.11   106.4  680.89     116  679.79   135.4  676.92   153.6   676.8
   171.8  674.95   215.8  671.18   224.2  670.88   242.2  671.39   250.9  670.82
   259.6  669.56   268.4  668.71   277.1  668.24   285.8  668.97   287.6  669.65
   294.5  672.28   303.2  676.01   312.1  677.62     321  677.12   329.9  677.12
   338.8  679.65   347.7  684.86   365.4  698.55   374.3  704.97   383.2     710
#Mann= 3 , 0 , 0
       0     .07       0   259.6    .045       0   287.6      .1       0
Bank Sta=259.6,287.6
XS Rating Curve= 0 ,0
Exp/Cntr=0.3,0.1

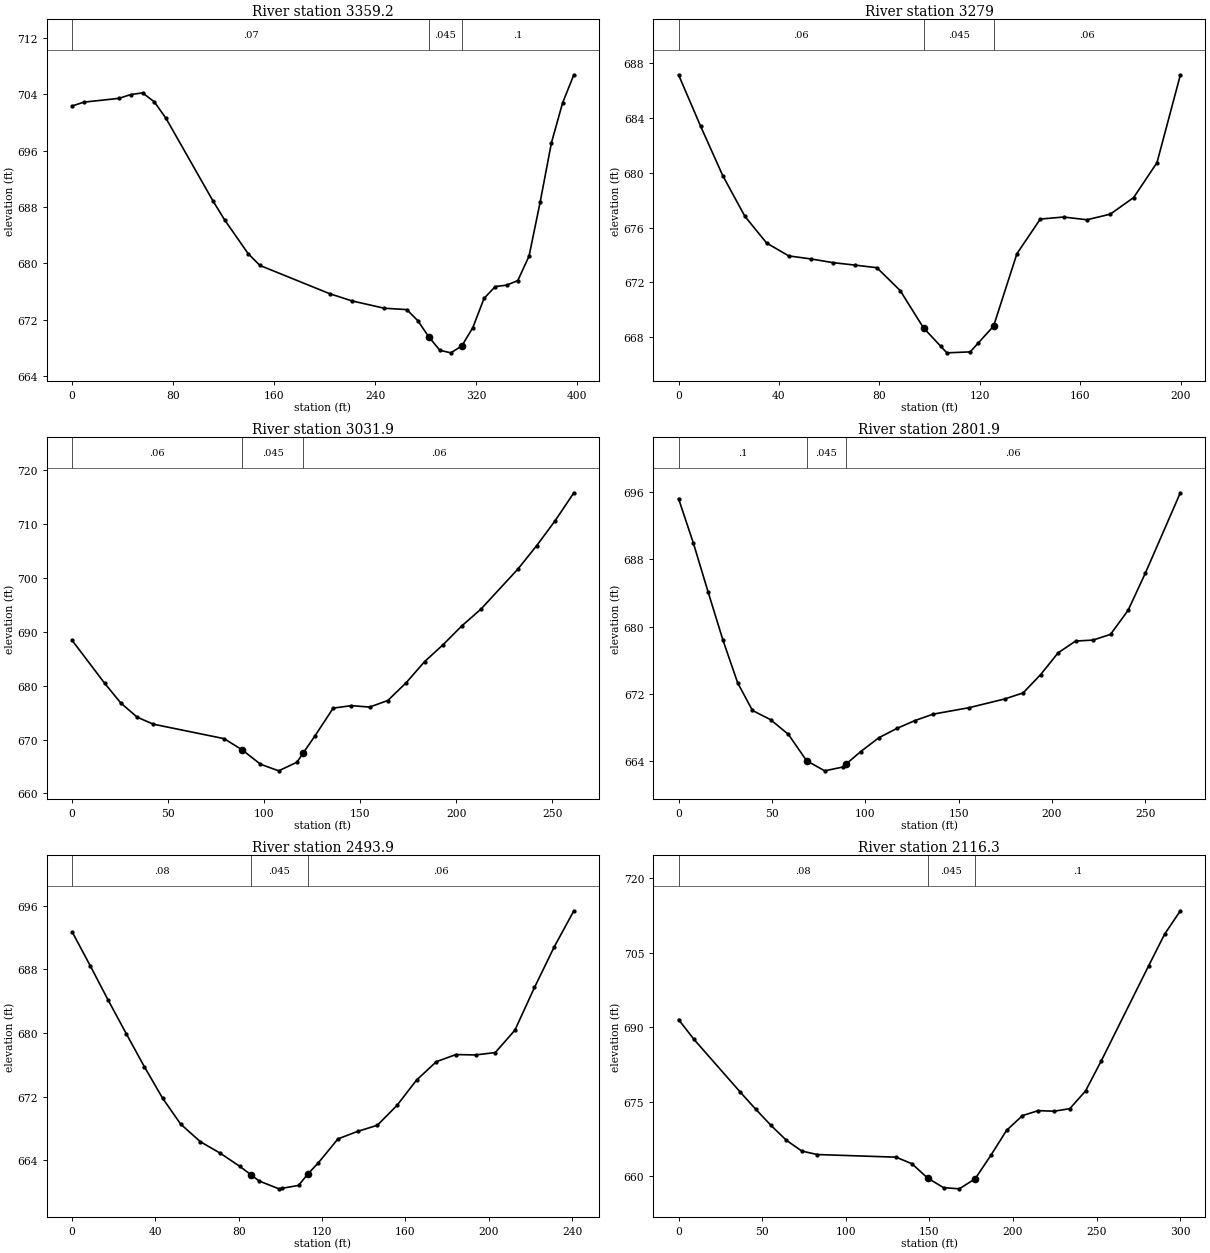
Type RM Length L Ch R = 1 ,3359.2  ,87,80.1,74.9
XS GIS Cut Line= 6
     1793876.485      540323.894     1794008.151      540393.003
     1794035.339      540451.498     1794059.645      540487.088
      1794106.52      540526.151       1794177.7      540562.609
#Sta/Elev= 30
       0  702.31     9.3  702.86    37.2   703.4    46.5  703.94    55.8  704.17
    65.1  702.91    74.4  700.56   111.5  688.88   120.8  686.17   139.4  681.39
   148.7  679.72     204  675.71   221.6  674.69   247.3  673.65     265  673.46
   273.7   671.9   282.5  669.58   291.2  667.69   299.9  667.33   308.6  668.31
   317.3   670.9   326.2  675.05   335.1  676.73     344  676.92   352.9  677.57
   361.8  681.03   370.6  688.68   379.5  697.07   388.4  702.77   397.3  706.74
#Mann= 3 , 0 , 0
       0     .07       0   282.5    .045       0   308.6      .1       0
Bank Sta=282.5,308.6
XS Rating Curve= 0 ,0
Exp/Cntr=0.3,0.1

Type RM Length L Ch R = 1 ,3279    ,245.8,247.1,248.4
XS GIS Cut Line= 3
      1793963.29       540575.63     1794042.283      540578.234
     1794152.526      540627.713
#Sta/Elev= 25
       0  687.16     8.8   683.4    17.6   679.8    26.4  676.83    35.1  674.87
    43.9  673.93    52.7  673.71    61.5  673.44    70.2  673.26      79  673.07
    88.3   671.4    97.6  668.67   104.4  667.34   106.9  666.85   116.2  666.92
   119.4  667.57   125.5   668.8   134.8  674.09   144.1  676.62   153.4  676.77
   162.7  676.57     172  676.98   181.3  678.19   190.6  680.74   199.9  687.14
#Mann= 3 , 0 , 0
       0     .06       0    97.6    .045       0   125.5     .06       0
Bank Sta=97.6,125.5
XS Rating Curve= 0 ,0
Exp/Cntr=0.3,0.1

Type RM Length L Ch R = 1 ,3031.9  ,227.2,230.1,232.2
XS GIS Cut Line= 4
     1793912.075        540785.7     1793959.818      540803.061
     1794069.193      540859.484     1794125.617      540926.325
#Sta/Elev= 25
       0  688.43    16.9  680.48    25.4  676.78    33.9  674.16    42.3  672.86
    79.2  670.17    88.7  668.06    98.1  665.43   107.6   664.2   117.1   665.8
   120.2  667.42   126.5   670.7     136  675.84   145.5   676.3   154.9  676.03
   164.4  677.25   173.9  680.52   183.6  684.48   193.3  687.64     203  691.11
   212.8  694.17   232.2  701.66   241.9  705.97   251.6  710.64   261.3   715.8
#Mann= 3 , 0 , 0
       0     .06       0    88.7    .045       0   120.2     .06       0
Bank Sta=88.7,120.2
XS Rating Curve= 0 ,0
Exp/Cntr=0.3,0.1

Type RM Length L Ch R = 1 ,2801.9  ,333.4,308,283.1
XS GIS Cut Line= 4
      1793825.27      540961.047      1793856.52      540985.352
     1793974.575      541069.554     1794058.776      541072.158
#Sta/Elev= 28
       0   695.2     7.9  689.96    15.8  684.15    23.8  678.39    31.7  673.31
    39.6  670.04    49.3  668.95    58.9  667.19    68.6  664.07    78.3  662.87
    87.9  663.32    89.8  663.68    97.6  665.16   107.3   666.8   116.9   667.9
   126.6  668.84   136.3   669.6   155.6  670.37   174.9  671.42   184.6  672.13
     194  674.31   203.3  676.88   212.7  678.29     222   678.4   231.4  679.08
   240.8  681.93   250.1  686.37   268.8   695.9
#Mann= 3 , 0 , 0
       0      .1       0    68.6    .045       0    89.8     .06       0
Bank Sta=68.6,89.8
XS Rating Curve= 0 ,0
Exp/Cntr=0.3,0.1

Type RM Length L Ch R = 1 ,2493.9  ,368.2,377.6,386.7
XS GIS Cut Line= 3
     1793828.742      541309.137     1793880.825      541307.401
     1794050.964      541225.804
#Sta/Elev= 30
       0  692.71     8.7  688.45    17.4  684.08    26.1  679.86    34.7  675.76
    43.4  671.83    52.1  668.56    61.6  666.34      71  664.92    80.4  663.27
    85.8   662.2    89.8  661.41    99.3  660.43   100.8   660.5   108.7  660.86
  113.15   662.3   118.2   663.7   127.6   666.7     137  667.64   146.5  668.41
   155.9   670.9   165.3  674.08   174.8  676.39   184.2  677.29   193.6  677.24
   203.1  677.54   212.5  680.35   221.9  685.71   231.4  690.82   240.8  695.34
#Mann= 3 , 0 , 0
       0     .08       0    85.8    .045       0  113.15     .06       0
Bank Sta=85.8,113.15
XS Rating Curve= 0 ,0
Exp/Cntr=0.3,0.1

Type RM Length L Ch R = 1 ,2116.3  ,295.1,308.7,322.4
XS GIS Cut Line= 3
     1793769.714      541692.818     1793847.839       541665.04
     1794064.853      541656.359
#Sta/Elev= 25
       0  691.54     9.2  687.56    36.8  676.97    46.1   673.5    55.3  670.22
    64.5  667.22    73.7  665.06    82.9  664.35   130.1  663.82   139.6  662.49
     149   659.6   158.5  657.68   167.9  657.44   177.4  659.47   186.8   664.2
   196.2  669.23   205.7  672.19   215.1  673.19   224.6  673.08     234  673.59
   243.4  677.15   252.9  683.27   281.2   702.4   290.7  708.73   300.1  713.45
#Mann= 3 , 0 , 0
       0     .08       0     149    .045       0   177.4      .1       0
Bank Sta=149,177.4
XS Rating Curve= 0 ,0
Exp/Cntr=0.3,0.1

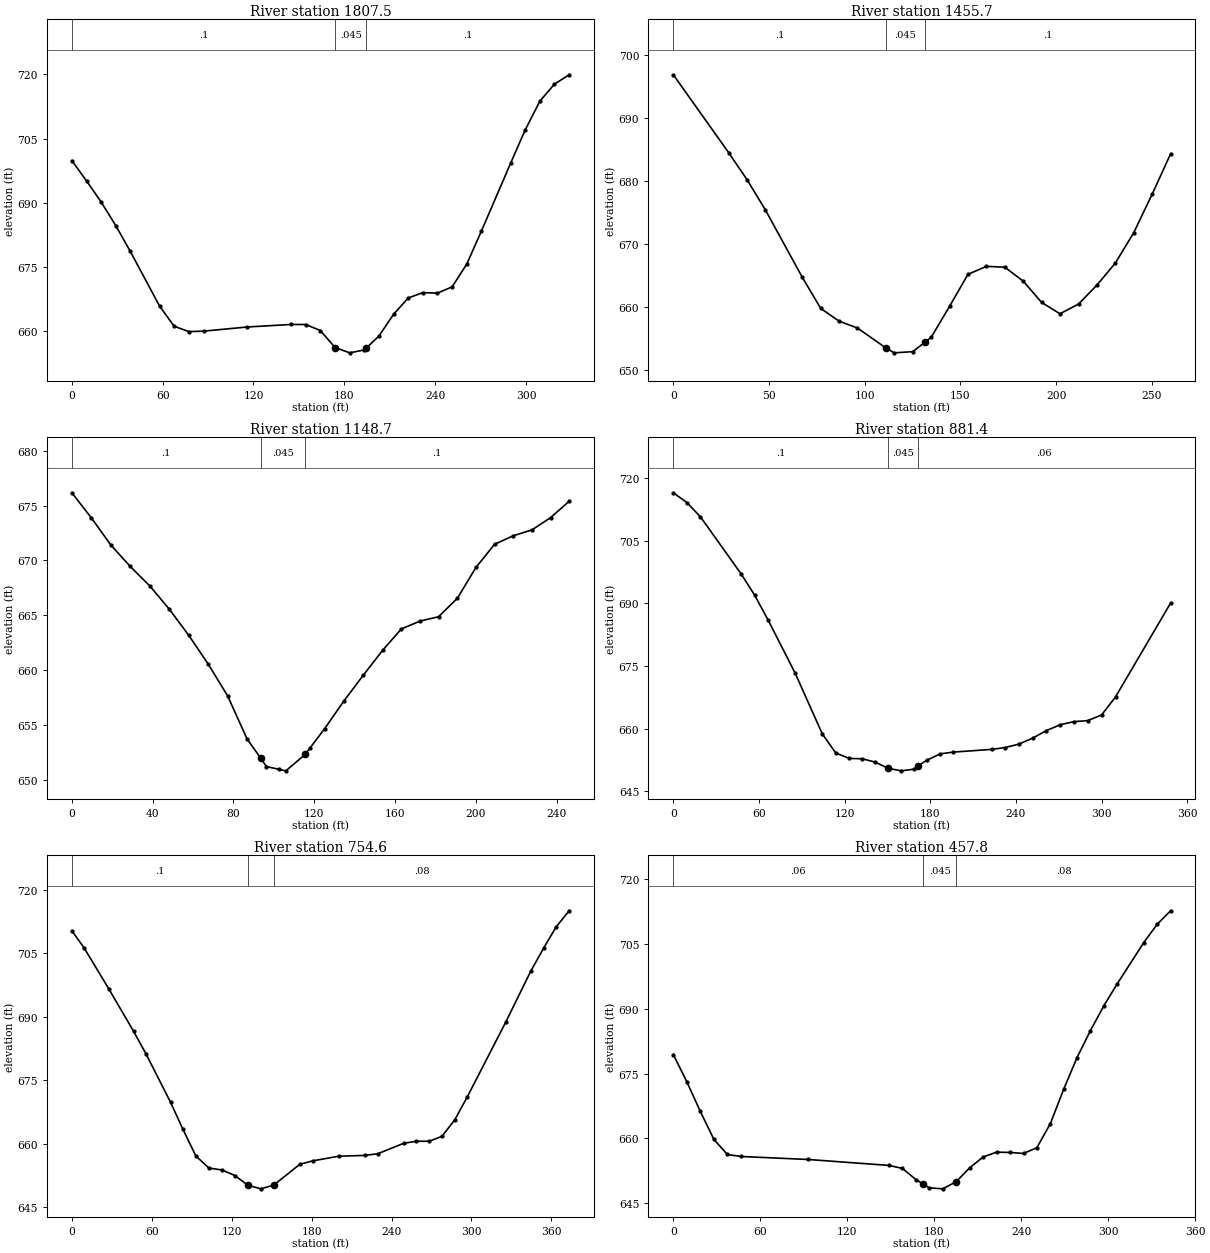
Type RM Length L Ch R = 1 ,1807.5  ,349.5,351.8,354.3
XS GIS Cut Line= 2
      1793700.27       541861.22     1793978.047      542036.568
#Sta/Elev= 30
       0  699.85     9.7  695.12    19.3  690.23      29   684.7    38.6  678.68
      58  665.89    67.6  661.21    77.3  659.96      87  660.07   115.9  661.04
   144.9  661.63   154.6  661.61   164.2  660.21   173.9  656.24   183.6  655.01
   193.2  655.69   194.6  656.16   202.9  658.94   212.6  664.04   222.2   667.8
   231.9  669.06   241.5  668.94   251.2   670.4   260.9  675.72   270.5  683.37
   289.8   699.2   299.5  707.01   309.2  713.73   318.8  717.68   328.5  719.87
#Mann= 3 , 0 , 0
       0      .1       0   173.9    .045       0   194.6      .1       0
Bank Sta=173.9,194.6
XS Rating Curve= 0 ,0
Exp/Cntr=0.3,0.1

Type RM Length L Ch R = 1 ,1455.7  ,307,307,306.8
XS GIS Cut Line= 2
     1793589.158      542177.193      1793794.02      542336.915
#Sta/Elev= 26
       0   696.8    28.9  684.46    38.5  680.18    48.1  675.38    67.4   664.7
      77  659.78    86.6  657.76    96.2  656.67  111.07  653.51   115.4  652.74
   125.1  652.93   131.3  654.39   134.7  655.19   144.3   660.1   153.9  665.17
   163.6  666.45   173.2   666.3   182.8   664.1   192.4  660.73     202  658.93
   211.7  660.47   221.3  663.47   230.9  666.96   240.5  671.76   250.2   677.9
   259.8  684.28
#Mann= 3 , 0 , 0
       0      .1       0  111.07    .045       0   131.3      .1       0
Bank Sta=111.07,131.3
XS Rating Curve= 0 ,0
Exp/Cntr=0.3,0.1

Type RM Length L Ch R = 1 ,1148.7  ,278.3,267.3,256.5
XS GIS Cut Line= 4
     1793408.603      542427.193     1793471.103      542472.332
     1793531.867      542519.207     1793622.145      542538.304
#Sta/Elev= 30
       0  676.16     9.6  673.89    19.3   671.4    28.9  669.45    38.6  667.67
    48.2  665.56    57.8  663.19    67.5  660.55    77.1  657.66    86.7  653.74
   93.45  651.99    96.3  651.22   102.7  650.96   105.9  650.83   115.5  652.33
   117.7  652.87   125.1  654.67   134.6  657.18   144.2  659.53   153.8  661.81
   163.1  663.76   172.3  664.47   181.5  664.87   190.8  666.55     200  669.36
   209.2  671.47   218.4  672.24   227.7  672.78   236.9  673.89   246.1  675.38
#Mann= 3 , 0 , 0
       0      .1       0   93.45    .045       0   115.5      .1       0
Bank Sta=93.45,115.5
XS Rating Curve= 0 ,0
Exp/Cntr=0.3,0.1

Type RM Length L Ch R = 1 ,881.4   ,126.7,126.8,126.4
XS GIS Cut Line= 4
     1793248.881      542711.915     1793370.122      542734.314
     1793477.343      542753.954     1793590.895      542777.887
#Sta/Elev= 30
       0  716.54     9.5   714.2      19  710.77    47.4  697.13    56.9  692.02
    66.4  686.01    85.4  673.24   104.3  658.75   113.8  654.14   123.3  652.85
   132.4  652.76   141.5  651.95   150.5  650.47   159.6  649.87   168.7  650.27
  171.12  651.02   177.8  652.46   186.9  653.94     196  654.36   223.2  655.02
   232.3  655.45     242  656.27   251.6   657.7   261.3  659.52     271  660.92
   280.6  661.67   290.3  661.91     300  663.29   309.7  667.58   348.3   690.1
#Mann= 3 , 0 , 0
       0      .1       0   150.5    .045       0  171.12     .06       0
Bank Sta=150.5,171.12
XS Rating Curve= 0 ,0
Exp/Cntr=0.3,0.1

Type RM Length L Ch R = 1 ,754.6   ,287,296.8,306.5
XS GIS Cut Line= 4
     1793252.353      542802.193     1793320.061      542850.804
     1793483.256      542880.318     1793601.311      542918.512
#Sta/Elev= 30
       0   710.3     9.3  706.19    27.8  696.53    46.3  686.55    55.6  681.23
    74.1  669.76    83.4  663.37    93.1  657.07   102.9  654.21   112.6  653.77
   122.4  652.45   132.1  650.16   141.9   649.3   151.6   650.2   171.2  655.11
   180.9  655.92   200.4  657.01   219.9   657.2   229.7   657.6   249.2  660.07
   258.7  660.54   268.3  660.55   277.8  661.71   287.4  665.58   296.9  671.06
   325.6  688.62   344.6  700.79   354.2   706.2   363.7  711.26   373.3  715.01
#Mann= 3 , 0 , 0
       0      .1       0   132.1    .045       0   151.6     .08       0
Bank Sta=132.1,151.6
XS Rating Curve= 0 ,0
Exp/Cntr=0.3,0.1

Type RM Length L Ch R = 1 ,457.8   ,72.7,78.4,84.1
XS GIS Cut Line= 4
     1793156.867      543012.262     1793221.103      543092.123
     1793342.631      543177.193     1793412.075      543237.957
#Sta/Elev= 29
       0   679.4     9.3  673.11    18.6  666.26      28  659.76    37.3  656.28
    46.6  655.82    93.2  655.12   148.8  653.75   158.1  653.05   167.4  650.47
   172.2  649.48   176.7  648.56   185.9  648.33   195.2  649.99   204.5  653.21
   213.8  655.71     223  656.82   232.3  656.75   241.6  656.52   250.8  657.84
   260.1   663.4   269.3  671.35   278.5  678.68   287.7   684.9     297  690.67
   306.2  695.75   324.6  705.33   333.9  709.59   343.1  712.68
#Mann= 3 , 0 , 0
       0     .06       0   172.2    .045       0   195.2     .08       0
Bank Sta=172.2,195.2
XS Rating Curve= 0 ,0
Exp/Cntr=0.3,0.1

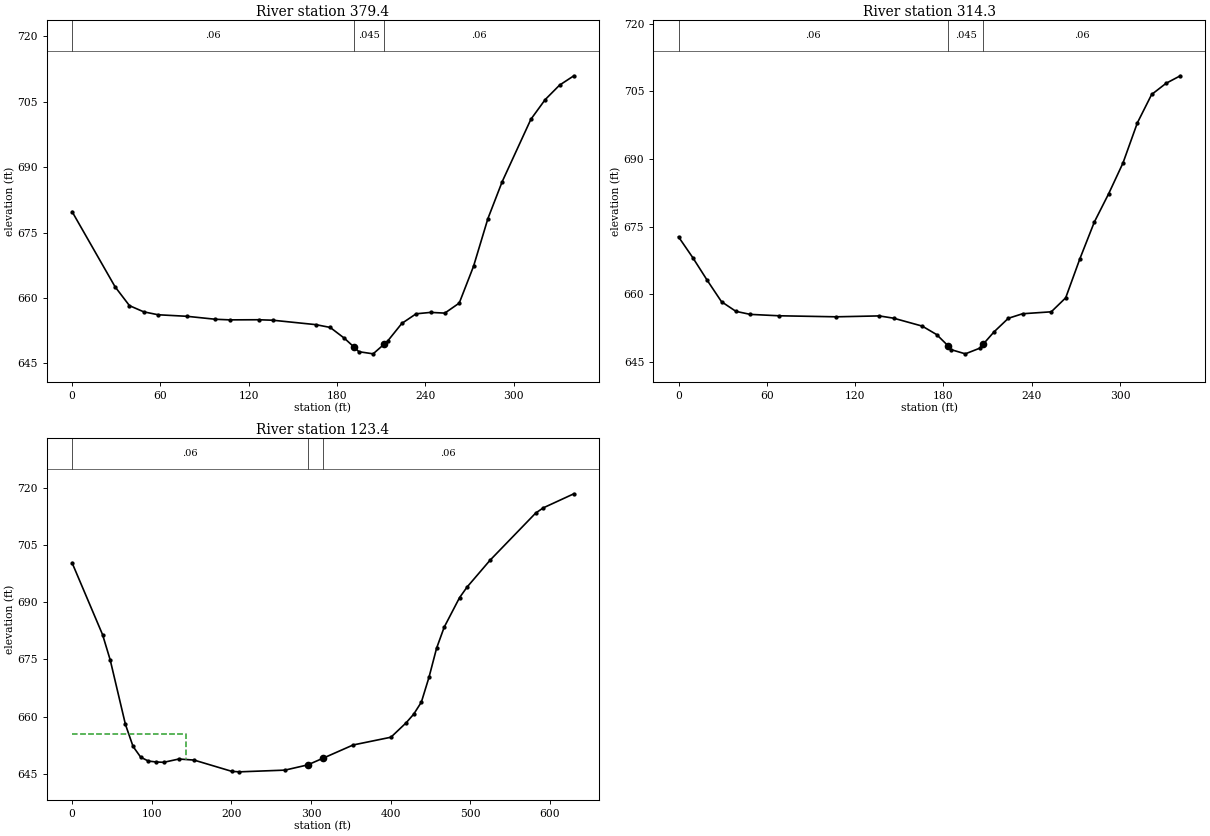
Type RM Length L Ch R = 1 ,379.4   ,65,65,65
XS GIS Cut Line= 2
     1793103.047      543041.776      1793325.27      543300.457
#Sta/Elev= 30
       0  679.79    29.2  662.58      39  658.25    48.7  656.83    58.5  656.16
      78  655.81    97.4  655.13   107.2  654.99   126.7  655.02   136.4  654.91
   165.6   653.9   175.4  653.26   185.1  650.77   191.9  648.67   194.9   647.7
   204.6  647.21     212   649.4   214.4  650.11   224.1  654.18   233.8  656.38
   243.6   656.7   253.3  656.54   263.1  658.83   272.8  667.24   282.6   678.2
   292.3  686.65   311.8  700.94   321.5  705.44   331.3  708.76     341   710.9
#Mann= 3 , 0 , 0
       0     .06       0   191.9    .045       0     212     .06       0
Bank Sta=191.9,212
XS Rating Curve= 0 ,0
Exp/Cntr=0.3,0.1

Type RM Length L Ch R = 1 ,314.3   ,236.3,191,175.2
XS GIS Cut Line= 2
     1793056.172      543086.915     1793278.395      543345.595
#Sta/Elev= 30
       0  672.73     9.7  668.12    19.5   663.1    29.2  658.36      39  656.22
    48.7  655.55    68.2  655.24   107.2  655.01   136.4  655.21   146.2   654.7
   165.6  652.95   175.4  651.07  183.22  648.57   185.1  647.74   194.9   646.8
   204.6  648.04   207.2     649   214.4  651.67   224.1  654.68   233.8  655.69
   253.3  656.12   263.1  659.22   272.8  667.93   282.6  676.05   292.3   682.3
     302  689.09   311.8  698.01   321.5   704.3   331.3  706.78     341  708.45
#Mann= 3 , 0 , 0
       0     .06       0  183.22    .045       0   207.2     .06       0
Bank Sta=183.22,207.2
XS Rating Curve= 0 ,0
Exp/Cntr=0.3,0.1

Type RM Length L Ch R = 1 ,123.4   ,68,123.4,149
XS GIS Cut Line= 4
     1792828.742       543173.72     1792889.506      543303.929
     1793148.186      543399.415      1793356.52      543368.165
#Sta/Elev= 30
       0  700.41    38.3  681.52    47.9  674.86      67  657.93    76.6  652.13
    86.2  649.31    95.8  648.29   105.4  648.06     115  647.96   134.1  648.83
   153.2  648.55   200.7  645.58   210.2  645.46   267.3  645.91   295.8  647.28
   314.6  648.99   352.9  652.52   400.4  654.56   419.4  658.33     429  660.62
   438.6  663.78   448.2  670.32   457.7  677.94   467.3   683.5   486.5  691.23
     496  694.03   524.8  701.07   582.2  713.49   591.8  714.86   630.1  718.55
#Mann= 3 , 0 , 0
       0     .06       0   295.8    .045       0   314.6     .06       0
#XS Ineff= 2 , 0
          143.27  655.33
Permanent Ineff=
       F       F
Bank Sta=295.8,314.6
XS Rating Curve= 0 ,0
Exp/Cntr=0.3,0.1

Chan Stop Cuts=-1
Use User Specified Reach Order=0
Composite Channel Slope=5